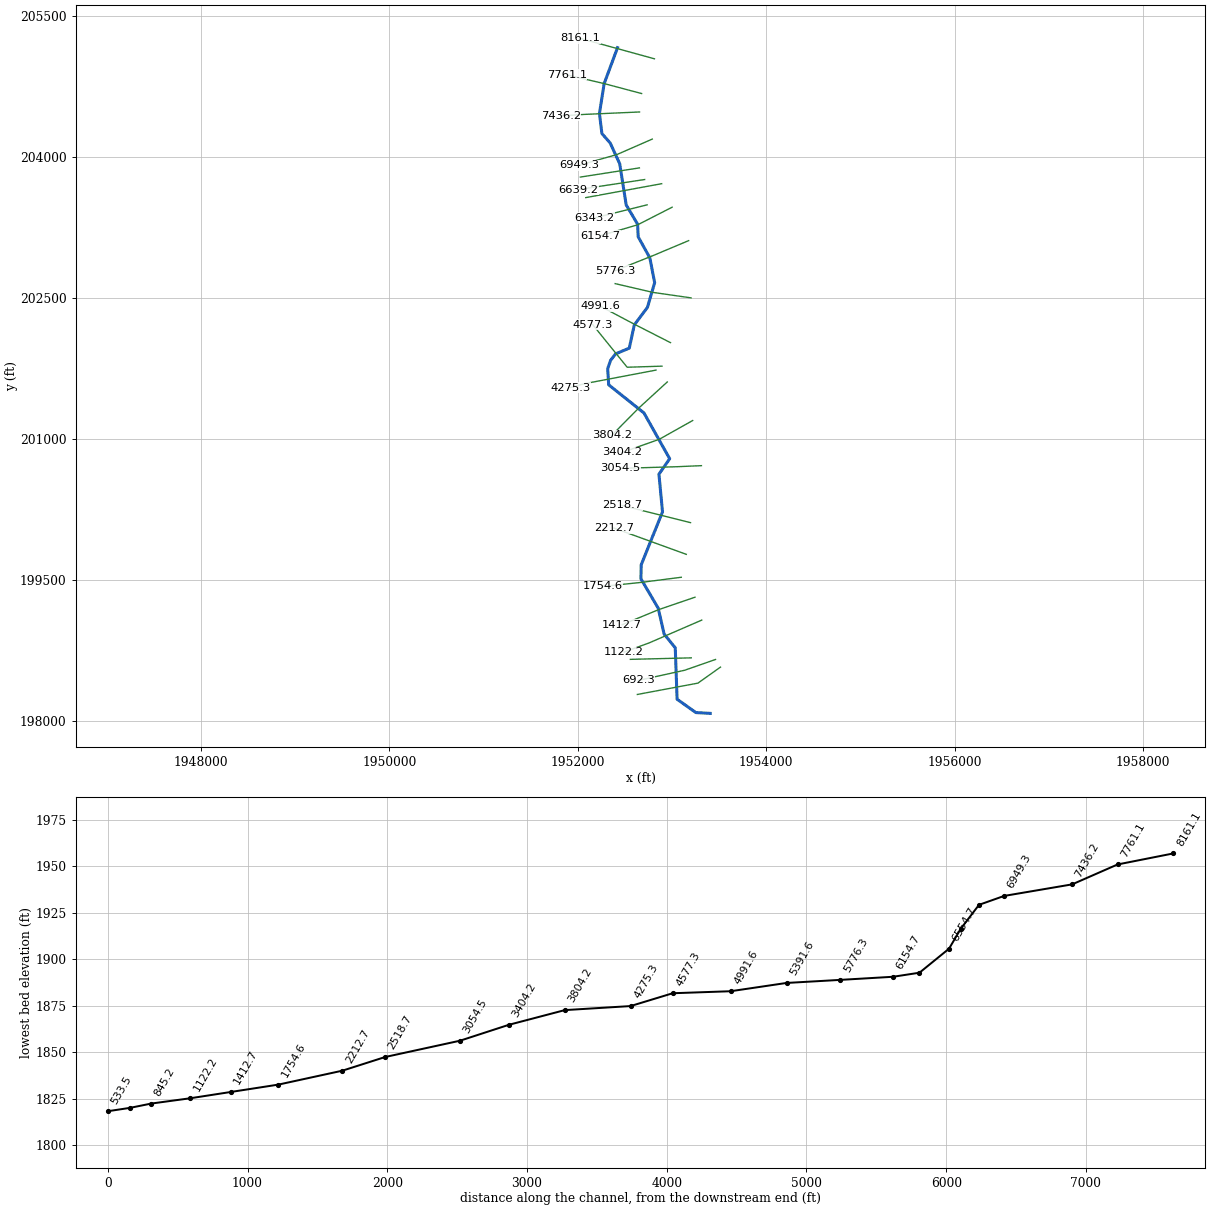
--- NrthFrk.prj (project) ---

Proj Title=NrthFrk
Current Plan=p01
Default Exp/Contr=0,0
English Units
Geom File=g01
Flow File=f01
Plan File=p01
BEGIN DESCRIPTION:
END DESCRIPTION:
DSS Export Rating Curves= 0
DSS Export Rating Curve Sorted= 0
DSS Export Volume Flow Curves= 0
DXF OffsetX= 0
DXF OffsetY= 0
DXF ScaleX= 0
DXF ScaleY= 0

--- NrthFrk.p01 (plan) ---

Plan Title=Floodplain
Program Version=4.00
Geom File=g01
Flow File=f01
K Sum by GR=0
Std Step Tol=0.01
Critical Tol=0.01
Num of Std Step Trials=20
Max Error Tol=0.3
Flow Tol Ratio=0.001
Split Flow NTrial=30
Split Flow Tol=0.02
Split Flow Ratio=0.02
Log Output Level=0
Friction Slope Method=1
Unsteady Friction Slope Method=2
Unsteady Bridges Friction Slope Method=1
Global Log Level=0
CheckData=False
Run HTab=0
Run UNet=0
Run PostProcess=0
UNET Theta=0
UNET Theta Warmup=0
UNET ZTol=0
UNET ZSATol=0
UNET MxIter=0
UNET MaxInSteps=0
UNET DtIC=0
UNET DtMin=0
UNET MaxCRTS=0
UNET WFStab=0
UNET SFStab=0
UNET WFX=0
UNET SFX=0
UNET DSS MLevel=0
UNET DZMax Abort=0
UNET Convert EG Bridges=0
UNET Use Existing IB Tables=0
UNET Froude Limit=0
UNET Froude Power=0
Write IC File=0
Echo Input=False
Echo Output=False
Write Detailed=0

--- NrthFrk.f01 (steady flow) ---

Flow Title=NFF Regression Equation
Program Version=4.00
Number of Profiles=1
Profile Names=P100yr
River Rch & RM=NrthFrk,Main      ,8161.1
1088.336
River Rch & RM=NrthFrk,Main      ,4275.3
1139.557
River Rch & RM=NrthFrk,Main      ,3804.2
1408.753
Boundary for River Rch & Prof#=NrthFrk,Main      ,1
Up Type=0
Dn Type=3
Dn Slope=0.014492

--- NrthFrk.g01 (geometry) ---

Geom Title=USGS 3m DEM
Program Version=4.10

River Reach=NrthFrk         ,Main
Reach XY= 30
     1952421.756      205162.179     1952279.588      204778.821
     1952229.756      204462.192     1952255.716      204248.686
     1952344.235       204147.15     1952445.003      203926.958
     1952513.964      203488.457     1952635.057       203284.03
     1952641.035      203150.007     1952764.701      202926.106
     1952816.047      202661.436     1952739.224      202398.613
     1952599.901      202212.415     1952546.516      201965.019
     1952400.536      201903.654      1952348.14      201835.237
     1952317.224      201746.142     1952327.907      201574.961
     1952702.766      201274.915     1952975.644      200788.208
       1952861.5      200624.222      1952899.38      200222.832
     1952672.818       199659.03     1952670.214      199510.592
     1952853.807      199198.092     1952916.307      198923.353
     1953034.797      198776.217     1953054.328      198229.342
     1953253.547      198087.415     1953406.044      198078.848

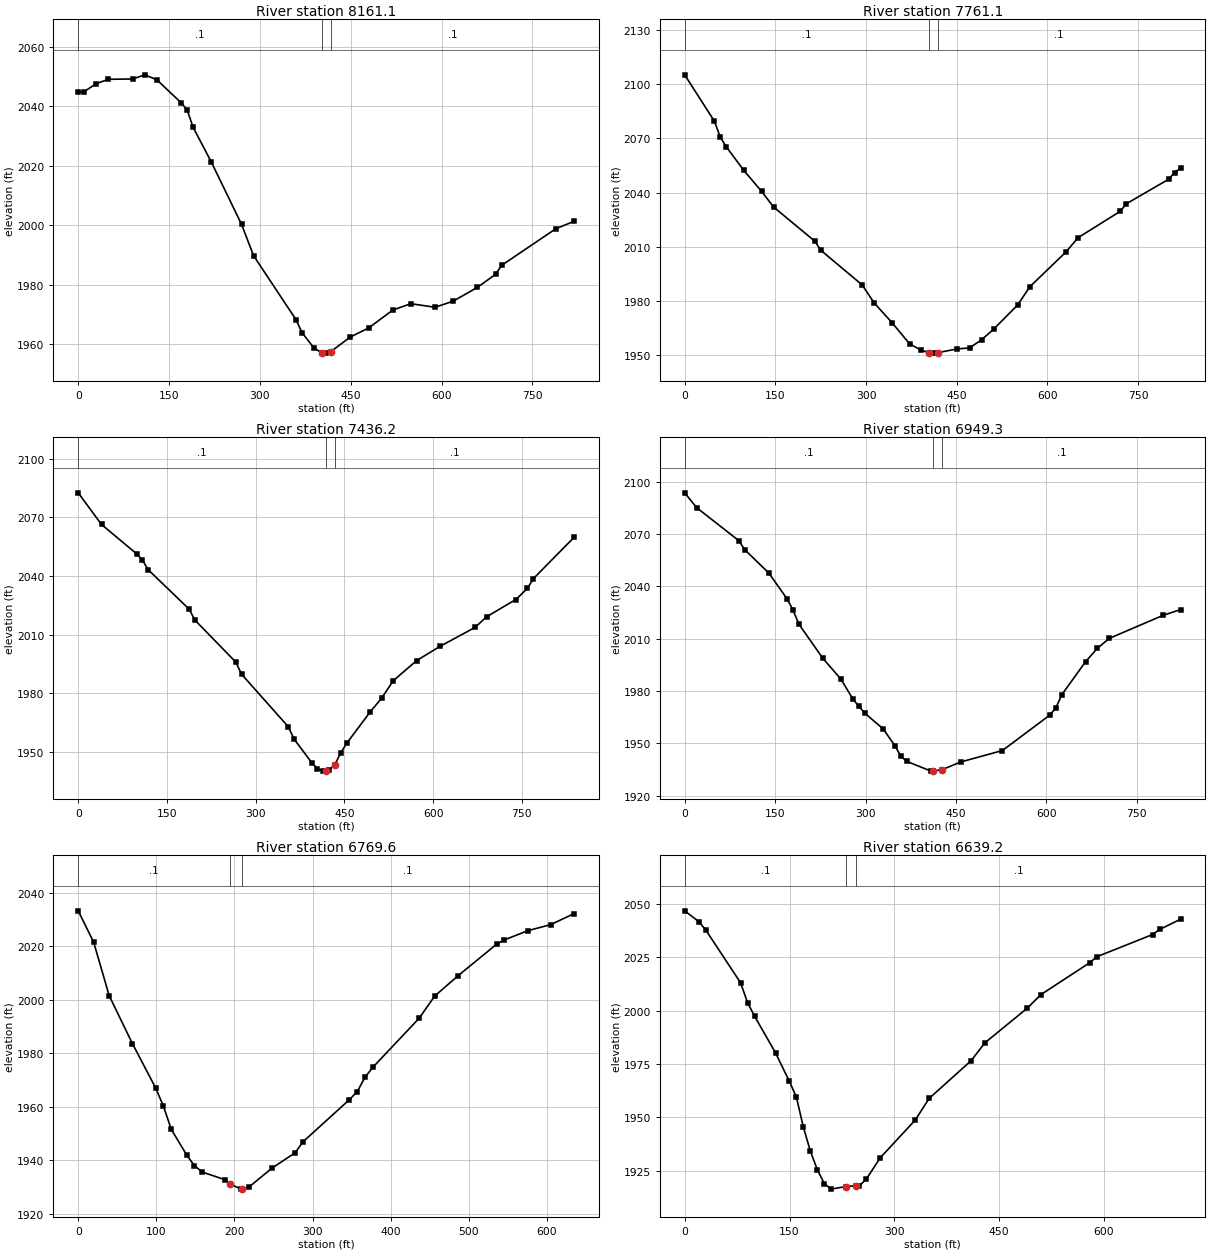
Type RM Length L Ch R = 1 ,8161.1  ,399.8,400,400.9
XS GIS Cut Line= 3
     1952813.851       205043.64     1952419.096      205152.539
     1952024.341      205261.437
#Sta/Elev= 30
       0  2044.7      10 2044.93      30 2047.59    49.9 2049.04    89.9 2049.14
   109.9 2050.54   129.8 2048.88   169.8 2041.18   179.8 2038.75   189.8 2032.87
   219.7 2021.26   269.7 2000.26   289.6 1989.72   359.6 1968.21   369.6 1963.84
   389.5 1958.62     402 1957.08   409.5 1956.94     417 1957.42   449.4 1962.37
   479.4 1965.37   519.4 1971.41   549.3 1973.57   589.3 1972.36   619.2 1974.42
   659.2 1979.04   689.2 1983.45   699.2 1986.46     789 1998.81     819 2001.28
#Mann= 3 , 0 , 0
       0      .1       0     402    .045       0     417      .1       0
Bank Sta=402,417
XS Rating Curve= 0 ,0
Exp/Cntr=0.3,0.1

Type RM Length L Ch R = 1 ,7761.1  ,318,324.9,331.1
XS GIS Cut Line= 3
      1952677.25      204674.064     1952279.912      204780.001
     1951881.618       204872.87
#Sta/Elev= 30
       0 2105.24      49 2079.61    58.8 2070.78    68.5 2065.48    97.9 2052.22
   127.3 2040.61   146.9 2032.01   215.4 2012.98   225.2 2007.98   293.7 1988.74
   313.3 1978.85   342.7 1967.95     372 1956.14   391.6  1952.5   403.7 1951.29
   411.2 1950.99   418.7 1951.29   451.1 1953.33   471.1 1953.86     491 1958.39
     511 1964.26   550.9 1977.76   570.8 1987.77   630.7  2007.1   650.6 2014.98
   720.4 2029.59   730.4 2033.77   800.2 2047.32   810.2 2051.05   820.2  2053.5
#Mann= 3 , 0 , 0
       0      .1       0   403.7    .045       0   418.7      .1       0
Bank Sta=403.7,418.7
XS Rating Curve= 0 ,0
Exp/Cntr=0.3,0.1

Type RM Length L Ch R = 1 ,7436.2  ,479.7,486.8,492.4
XS GIS Cut Line= 3
     1952655.574      204477.924     1952064.358       204451.76
     1951818.327      204436.139
#Sta/Elev= 30
       0 2082.56    39.4 2066.37    98.6 2051.42   108.5 2048.21   118.4  2043.2
   187.4 2023.12   197.3 2017.49   266.3 1996.04   276.2  1989.8   355.1 1962.98
   364.9 1956.68   394.5 1944.68   404.4 1941.48   414.3 1940.29   418.3 1940.58
   424.1 1941.01   433.3 1943.31   443.8 1949.65   453.7 1954.47   493.2 1970.44
   512.9 1977.61   532.6 1986.53   572.1 1996.81   611.5 2004.06   670.7 2013.74
   690.4 2019.21   739.7 2028.02   759.4 2033.72   769.3 2038.67   838.3 2059.85
#Mann= 3 , 0 , 0
       0      .1       0   418.3    .045       0   433.3      .1       0
Bank Sta=418.3,433.3
XS Rating Curve= 0 ,0
Exp/Cntr=0.3,0.1

Type RM Length L Ch R = 1 ,6949.3  ,184.2,179.7,176.8
XS GIS Cut Line= 3
     1952790.696      204189.493     1952416.361      204025.383
     1952018.321      203912.004
#Sta/Elev= 30
       0 2093.55    19.9 2085.04    89.7 2066.17    99.7 2060.93   139.6 2047.57
   169.5 2032.95   179.4 2026.65   189.4 2018.29   229.3 1998.66   259.2 1986.77
   279.1 1975.31   289.1 1971.17   299.1 1967.14     329 1958.36   348.9 1948.58
   358.9 1942.46   368.8 1939.59   408.7 1934.07   412.4 1934.11   427.4 1934.98
     458 1939.33     527 1945.87   605.8 1966.23   615.7 1970.35   625.5 1977.83
   664.9 1996.76   684.6 2004.51   704.4 2010.15     793 2023.28   822.6 2026.66
#Mann= 3 , 0 , 0
       0      .1       0   412.4    .045       0   427.4      .1       0
Bank Sta=412.4,427.4
XS Rating Curve= 0 ,0
Exp/Cntr=0.3,0.1

Type RM Length L Ch R = 1 ,6769.6  ,130.5,130.5,130.4
XS GIS Cut Line= 2
     1952654.052      203882.894     1952026.608      203785.262
#Sta/Elev= 30
       0 2033.32    19.8 2021.58    39.7 2001.55    69.4  1983.7    99.2 1967.06
   109.1  1960.3   119.1 1951.66   138.9 1942.02   148.8 1938.06   158.8 1935.67
   188.5 1932.74   194.7 1931.17   208.4 1929.28   209.7 1929.37   218.3 1929.97
     248 1937.11   277.8 1942.88   287.7 1946.95   347.3 1962.74   357.2 1965.72
   367.1 1971.03     377 1974.75   436.6 1993.18   456.4 2001.45   486.2 2009.02
   535.8 2020.86   545.7 2022.46   575.5 2025.87   605.2 2028.19     635  2032.3
#Mann= 3 , 0 , 0
       0      .1       0   194.7    .045       0   209.7      .1       0
Bank Sta=194.7,209.7
XS Rating Curve= 0 ,0
Exp/Cntr=0.3,0.1

Type RM Length L Ch R = 1 ,6639.2  ,83.4,84.1,84.8
XS GIS Cut Line= 2
     1952710.028      203759.227     1952008.383      203652.484
#Sta/Elev= 30
       0  2046.8      20 2041.79      30  2037.9      80  2013.1      90 2003.75
     100 1997.46     130 1980.27   149.9 1966.87   159.9 1959.49   169.9 1945.41
   179.9 1934.18   189.9 1925.47   199.9 1918.97   209.9 1916.43   230.7 1917.65
   245.7 1918.02   249.9 1917.96   259.9 1921.14   279.9 1931.12   329.9 1948.78
   349.9 1958.94   409.8 1976.57   429.8 1985.01   489.8 2001.08   509.8 2007.56
   579.8 2022.53   589.8 2025.29   669.7 2035.71   679.7 2038.06   709.7 2042.91
#Mann= 3 , 0 , 0
       0      .1       0   230.7    .045       0   245.7      .1       0
Bank Sta=230.7,245.7
XS Rating Curve= 0 ,0
Exp/Cntr=0.3,0.1

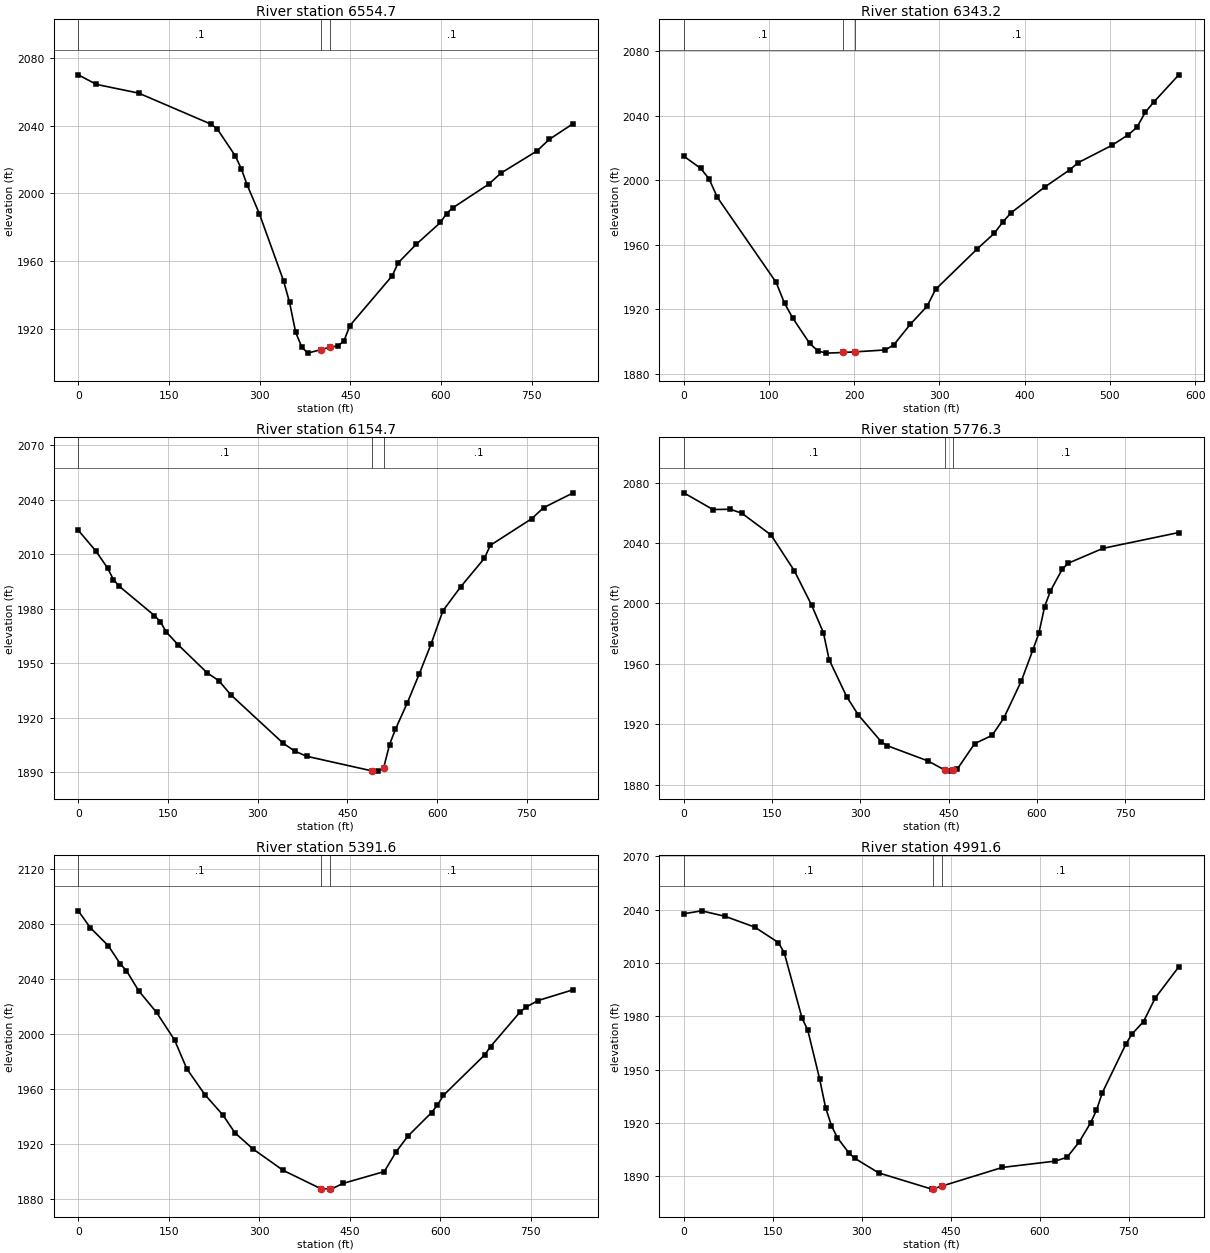
Type RM Length L Ch R = 1 ,6554.7  ,210,211.5,212.9
XS GIS Cut Line= 3
     1952890.206      203714.631     1952487.444      203640.653
     1952084.681      203566.676
#Sta/Elev= 30
       0 2070.02      30 2064.37    99.9 2059.22   219.7 2040.87   229.7 2038.18
   259.7 2022.21   269.7 2014.57   279.7 2004.71   299.6    1988   339.6  1948.4
   349.6 1935.61   359.6 1918.05   369.6 1909.41   379.5 1905.69     402 1907.79
     417 1909.28   429.5 1909.92   439.5 1912.85   449.4 1921.95   519.4 1951.35
   529.4 1959.06   559.3 1969.98   599.3 1982.86   609.3  1988.1   619.2 1991.39
   679.2 2005.48   699.2 2011.96   759.1 2025.11     779 2031.84     819 2041.26
#Mann= 3 , 0 , 0
       0      .1       0     402    .045       0     417      .1       0
Bank Sta=402,417
XS Rating Curve= 0 ,0
Exp/Cntr=0.3,0.1

Type RM Length L Ch R = 1 ,6343.2  ,182.5,188.5,189.7
XS GIS Cut Line= 2
     1952736.063      203489.765     1952172.404      203349.175
#Sta/Elev= 30
       0 2015.01    19.7  2007.5    29.5 2001.05    39.4 1989.42   108.3 1936.72
   118.2 1923.71     128 1914.39   147.7 1898.81   157.5 1894.08   167.4 1892.78
   186.4 1893.17   201.4 1893.59   236.3 1894.74   246.2 1897.79   265.8 1910.68
   285.5  1921.9   295.4 1932.32   344.6 1957.62   364.3 1967.12   374.2 1974.06
     384 1979.88   423.4  1995.8   452.9 2006.58   462.8 2010.99   502.2  2021.7
   521.8 2028.38   531.7 2032.93   541.5 2042.24   551.4 2048.53   580.9 2065.52
#Mann= 3 , 0 , 0
       0      .1       0   186.4    .045       0   201.4      .1       0
Bank Sta=186.4,201.4
XS Rating Curve= 0 ,0
Exp/Cntr=0.3,0.1

Type RM Length L Ch R = 1 ,6154.7  ,381,378.5,380.8
XS GIS Cut Line= 3
     1953001.534      203464.561     1952635.255      203277.103
     1952235.753      203160.301
#Sta/Elev= 30
       0 2023.17    29.4 2011.74      49 2002.37    58.8 1995.98    68.6 1992.32
   127.4 1976.22   137.2 1972.86     147 1967.21   166.5  1960.3   215.5 1944.71
   235.1 1940.36   254.7 1932.73   342.9 1905.85   362.5 1901.54   382.1 1898.76
   490.7 1890.76   500.6  1890.6   510.6 1892.37   520.5 1905.23   530.4 1913.69
   550.2 1928.21     570 1943.97   589.8 1960.47   609.7 1978.84   639.4 1992.04
     679 2007.72     689  2014.9   758.3 2029.57   778.1 2035.63   827.7 2043.79
#Mann= 3 , 0 , 0
       0      .1       0   490.7    .045       0   510.6      .1       0
Bank Sta=490.7,510.6
XS Rating Curve= 0 ,0
Exp/Cntr=0.3,0.1

Type RM Length L Ch R = 1 ,5776.3  ,396.4,384.5,370.8
XS GIS Cut Line= 3
     1953176.771       203108.86     1952803.672      202951.767
     1952398.826      202789.902
#Sta/Elev= 30
       0 2073.23    49.4 2062.16      79 2062.35    98.7 2059.68   148.1 2045.32
   187.6 2021.67   217.2 1998.76     237  1980.7   246.8 1962.81   276.5 1938.32
   296.2 1926.21   335.7 1908.22   345.6 1905.75   414.7 1895.68   442.8 1889.72
   454.4 1888.92   457.8 1889.35   464.3 1890.16     494 1907.13   523.7 1912.61
   543.6  1924.1   573.3 1948.63   593.1 1969.39     603 1980.13   612.9  1997.9
   622.8  2008.3   642.6 2022.52   652.6 2026.56     712 2036.46   840.8 2046.94
#Mann= 3 , 0 , 0
       0      .1       0   442.8    .045       0   457.8      .1       0
Bank Sta=442.8,457.8
XS Rating Curve= 0 ,0
Exp/Cntr=0.3,0.1

Type RM Length L Ch R = 1 ,5391.6  ,407.5,400,394
XS GIS Cut Line= 3
     1953202.569      202499.866     1952797.514      202558.161
     1952397.197      202651.418
#Sta/Elev= 30
       0 2089.88      20 2077.55    49.9 2064.36    69.9 2051.04    79.8 2046.32
    99.8 2031.84   129.8 2015.86   159.7 1995.73   179.7 1974.99   209.6 1956.14
   239.6 1941.27   259.5 1928.32   289.4 1916.54   339.4 1900.96   401.7 1887.63
   416.7 1887.33     419 1887.27   438.6 1891.41   507.1 1900.05   526.7 1914.41
   546.2 1925.84   585.4    1943   595.2 1948.48     605 1955.53   673.5 1984.99
   683.2 1991.09   732.2 2016.23     742 2019.76   761.6 2024.52   820.3 2032.45
#Mann= 3 , 0 , 0
       0      .1       0   401.7    .045       0   416.7      .1       0
Bank Sta=401.7,416.7
XS Rating Curve= 0 ,0
Exp/Cntr=0.3,0.1

Type RM Length L Ch R = 1 ,4991.6  ,421.6,414.3,408.1
XS GIS Cut Line= 3
     1952984.033      202023.463      1952603.15      202218.149
     1952244.114      202408.203
#Sta/Elev= 30
       0 2037.66    29.8 2039.33    69.6 2036.23   119.4 2030.19   159.2  2021.5
   169.1 2015.85     199 1979.19   208.9 1972.13   228.8 1944.78   238.8 1928.72
   248.7 1918.53   258.6 1911.77   278.5 1902.98   288.5 1900.06   328.3 1891.95
   417.8 1882.82   420.3 1883.05   435.3 1884.58   536.8 1895.03   625.9 1898.58
   645.7 1900.74   665.6 1909.09   685.4 1920.08   695.3 1927.26   705.2 1937.08
   744.8 1964.38   754.7 1969.88   774.5 1977.04   794.4 1990.38     834 2007.84
#Mann= 3 , 0 , 0
       0      .1       0   420.3    .045       0   435.3      .1       0
Bank Sta=420.3,435.3
XS Rating Curve= 0 ,0
Exp/Cntr=0.3,0.1

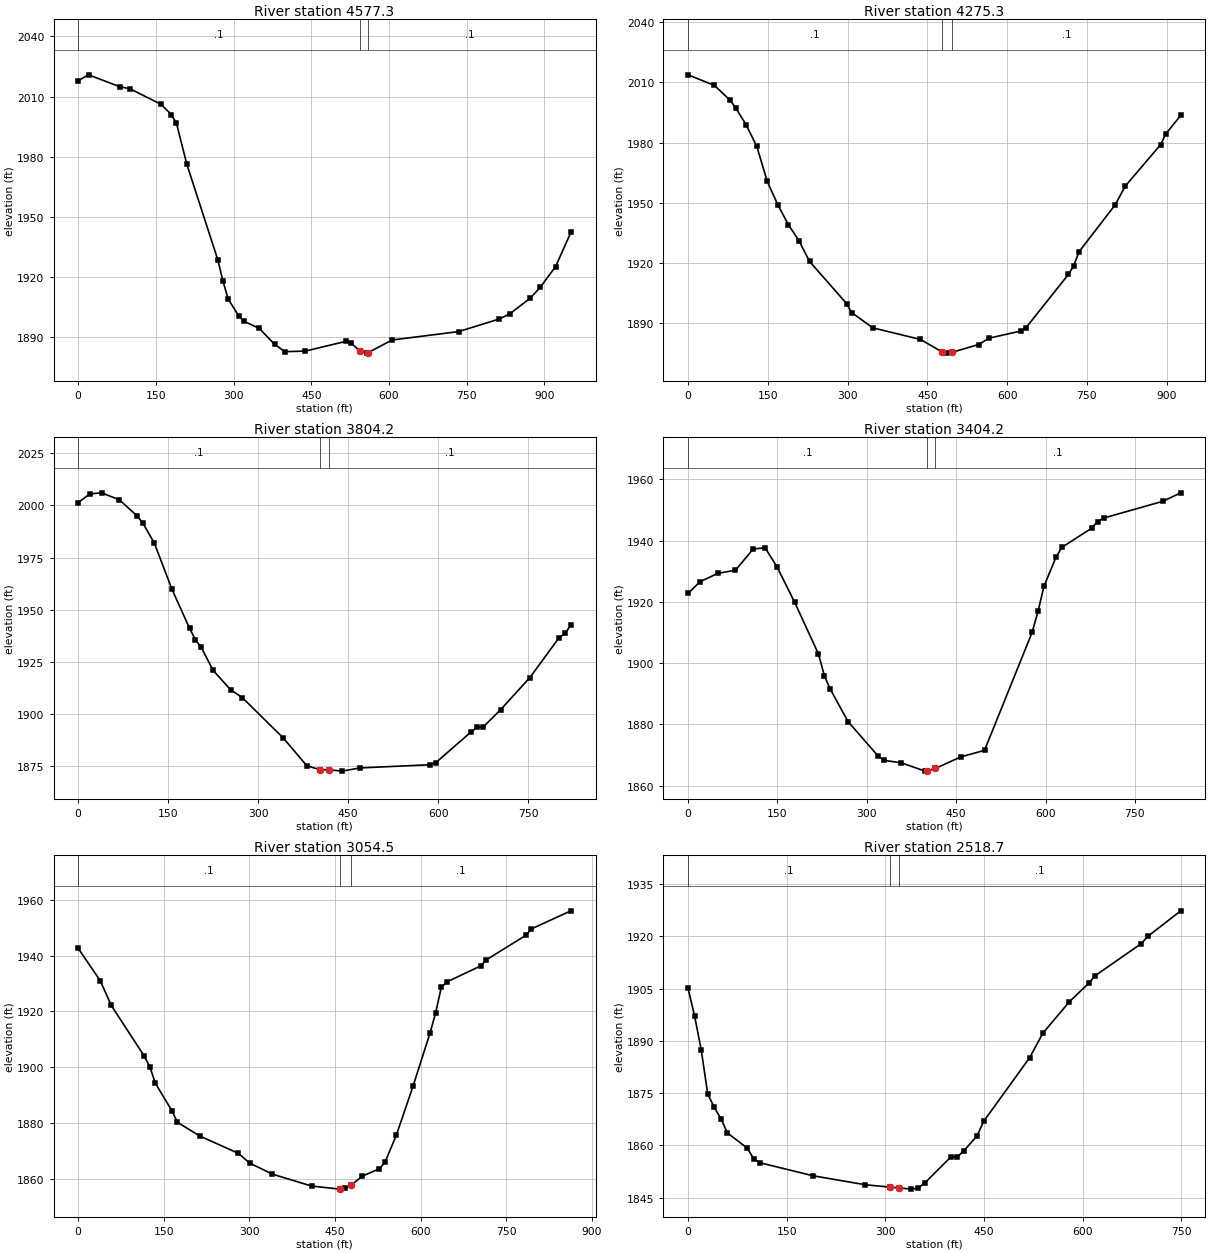
Type RM Length L Ch R = 1 ,4577.3  ,278.6,301.6,323.8
XS GIS Cut Line= 3
     1952893.555      201773.363     1952524.192      201761.831
      1952158.65      202214.416
#Sta/Elev= 30
       0  2017.9      20 2020.84    79.9 2014.93    99.9 2013.88   159.8 2006.12
   179.8 2001.01   189.8 1996.57   209.7 1976.21   269.7 1928.28   279.6 1917.63
   289.6  1908.8   309.6 1900.45   319.6 1897.73   349.6 1894.11   379.4  1886.1
   399.1 1882.46   438.6 1882.76   517.4 1887.66   527.3 1886.73   543.9 1882.73
   556.9 1881.74   558.9 1881.88   606.2 1888.32   734.4  1892.5   813.3 1898.82
     833 1901.32   872.4 1909.13   892.2 1914.65   921.7 1925.01   951.3 1942.12
#Mann= 3 , 0 , 0
       0      .1       0   543.9    .045       0   558.9      .1       0
#XS Ineff= 2 , 0
          517.38 1887.63
Permanent Ineff=
       F       F
Bank Sta=543.9,558.9
XS Rating Curve= 0 ,0
Exp/Cntr=0.3,0.1

Type RM Length L Ch R = 1 ,4275.3  ,458.2,471,484.7
XS GIS Cut Line= 3
     1952829.894      201731.261     1952068.856      201586.455
     1951922.441      201546.231
#Sta/Elev= 30
       0 2013.79    49.7 2008.48    79.5 2000.99    89.4 1997.35   109.2 1988.82
   129.1 1978.19     149 1960.54   168.8  1948.9   188.7 1938.96   208.6 1930.98
   228.4 1920.64     298 1899.61   307.9 1895.03   347.6 1887.44     437 1881.68
   476.7  1875.6   486.7 1874.84   496.6 1875.25   546.3 1879.14   566.1 1882.32
   625.7 1885.87   635.6 1887.56   715.1 1914.11     725 1918.32     735 1925.39
   803.2 1948.89   822.1 1958.23   888.6 1978.92   898.1  1984.2   926.5 1993.54
#Mann= 3 , 0 , 0
       0      .1       0   476.7    .045       0   496.6      .1       0
Bank Sta=476.7,496.6
XS Rating Curve= 0 ,0
Exp/Cntr=0.3,0.1

Type RM Length L Ch R = 1 ,3804.2  ,405.3,400,389.8
XS GIS Cut Line= 3
     1952950.061      201605.349     1952647.679      201327.826
     1952358.874      201035.663
#Sta/Elev= 30
       0 2001.33    19.5 2005.49    39.1    2006    68.4 2002.68    97.7 1995.09
   107.5 1991.65     127 1981.86   156.4 1959.73   185.7 1941.04   195.4  1935.6
   205.2 1931.95   224.8 1920.96   254.1 1911.64   273.6 1907.87     342  1888.5
   381.1  1875.2   402.9 1873.38   417.9 1873.32   439.8 1872.66   469.1 1874.18
   586.5 1875.73   596.3 1876.79     655 1891.49   664.7 1893.58   674.5 1893.68
   703.9 1902.06   752.8 1917.47   801.7 1936.67   811.5 1938.63   821.2 1942.75
#Mann= 3 , 0 , 0
       0      .1       0   402.9    .045       0   417.9      .1       0
Bank Sta=402.9,417.9
XS Rating Curve= 0 ,0
Exp/Cntr=0.3,0.1

Type RM Length L Ch R = 1 ,3404.2  ,358.1,349.6,344.3
XS GIS Cut Line= 3
     1953219.757      201194.874     1952864.461      200994.761
     1952469.236      200854.799
#Sta/Elev= 30
       0 1922.75    19.9 1926.52    49.7 1929.27    79.6 1930.32   109.4 1937.24
   129.3 1937.62   149.2 1931.47     179 1919.82   218.8 1903.03   228.8 1895.91
   238.7 1891.49   268.5 1880.94   318.3 1869.83   328.2 1868.31     358 1867.46
   397.8 1864.76   400.3 1864.78   415.3 1865.65   457.7  1869.4   497.6 1871.54
   577.5 1910.03   587.5    1917   597.4 1925.08   617.4  1934.5   627.4 1937.76
   677.3 1944.01   687.3 1946.19   697.3 1947.31   797.1 1952.81     827 1955.56
#Mann= 3 , 0 , 0
       0      .1       0   400.3    .045       0   415.3      .1       0
Bank Sta=400.3,415.3
XS Rating Curve= 0 ,0
Exp/Cntr=0.3,0.1

Type RM Length L Ch R = 1 ,3054.5  ,545.8,535.7,526
XS GIS Cut Line= 3
     1953312.686      200714.637     1953052.035      200703.375
     1952450.284      200685.676
#Sta/Elev= 30
       0  1942.7    38.6 1931.06      58 1922.16     116  1903.9   125.6 1900.06
   135.3 1894.17   164.3  1884.3   173.9  1880.2   212.6 1875.32   280.6 1869.05
   300.4 1865.57   339.8 1861.61   408.9 1857.31   458.3 1856.21   468.1 1856.44
     478 1857.62   497.8 1860.92   527.4  1863.5   537.2 1865.83     557 1875.47
   586.6 1893.29   616.2 1912.29     626  1919.5   635.9 1928.67   645.8 1930.64
     705 1936.37   714.9 1938.57     784 1947.36   793.8 1949.67   862.9 1956.15
#Mann= 3 , 0 , 0
       0      .1       0   458.3    .045       0     478      .1       0
Bank Sta=458.3,478
XS Rating Curve= 0 ,0
Exp/Cntr=0.3,0.1

Type RM Length L Ch R = 1 ,2518.7  ,308.3,306,303.7
XS GIS Cut Line= 2
     1953196.841      200108.059     1952470.437      200290.902
#Sta/Elev= 30
       0 1905.11      10  1897.1      20 1887.47      30 1874.69      40 1870.88
    49.9 1867.69    59.9 1863.55    89.9 1859.24    99.9 1856.13   109.9 1854.99
   189.8 1851.28   269.7 1848.69   306.4 1848.03   321.4 1847.77   339.6 1847.44
   349.6 1847.73   359.6 1849.14   399.5 1856.66   409.5 1856.71   419.5 1858.49
   439.4 1862.74   449.4 1866.89   519.4  1885.2   539.3 1892.19   579.3 1901.15
   609.2 1906.57   619.2 1908.76   689.1 1917.94   699.1 1920.04   749.1 1927.35
#Mann= 3 , 0 , 0
       0      .1       0   306.4    .045       0   321.4      .1       0
Bank Sta=306.4,321.4
XS Rating Curve= 0 ,0
Exp/Cntr=0.3,0.1

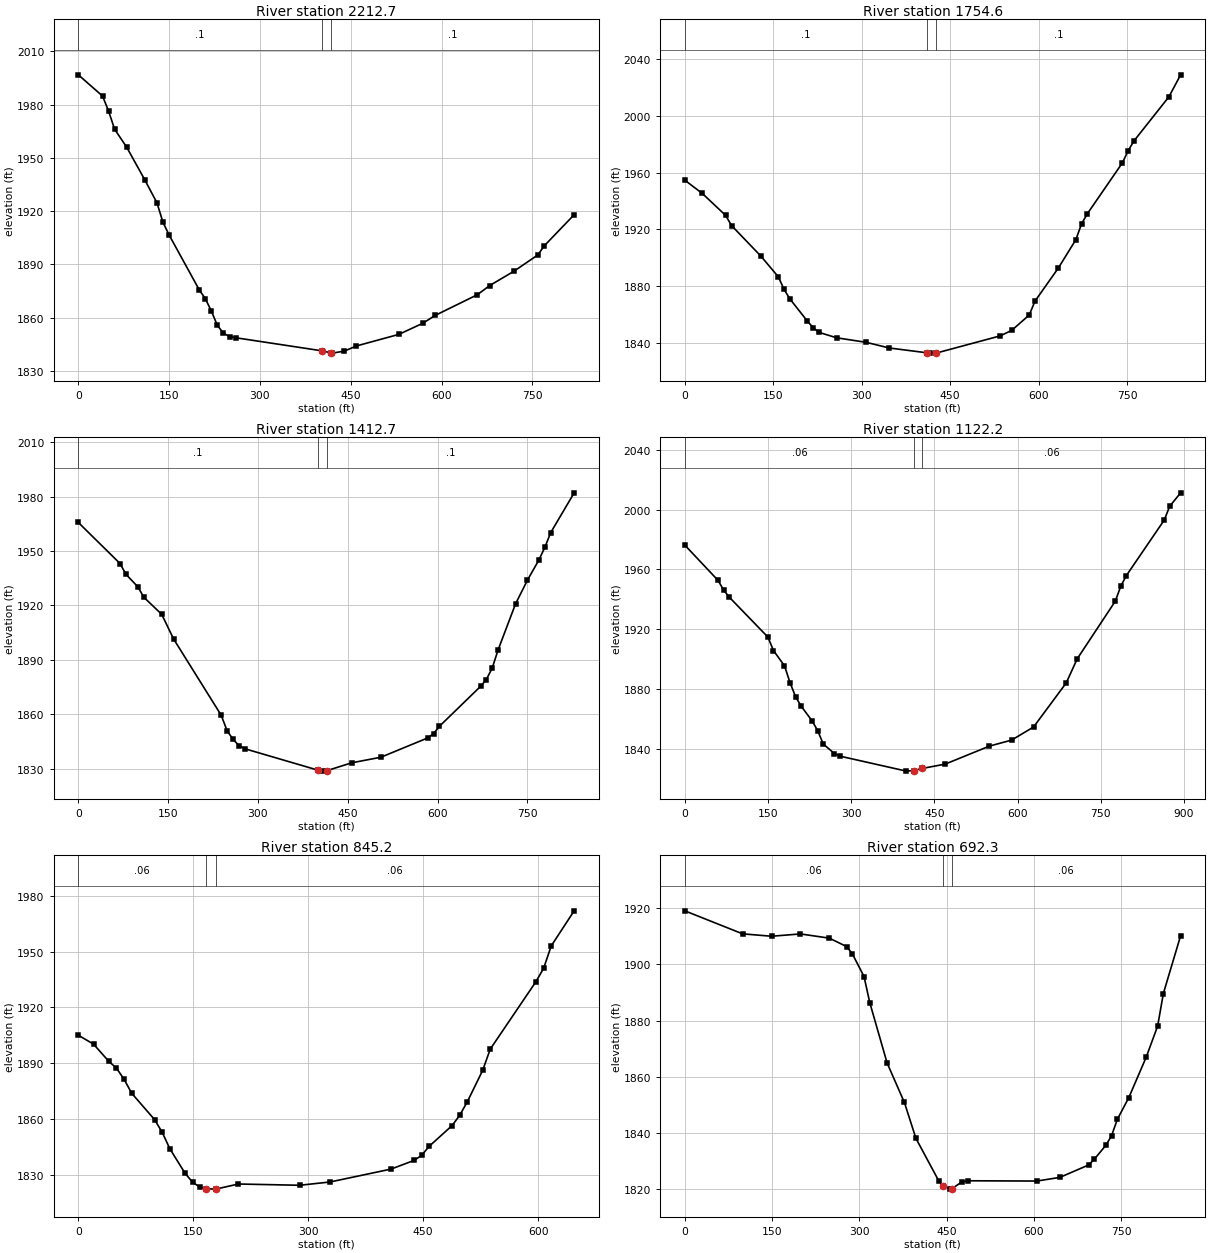
Type RM Length L Ch R = 1 ,2212.7  ,447.4,458.1,468.7
XS GIS Cut Line= 3
     1953151.803      199771.135     1952766.958      199911.078
     1952382.112      200051.022
#Sta/Elev= 30
       0 1996.73      40 1984.79    49.9 1976.39    59.9 1966.12    79.9 1955.99
   109.9 1937.53   129.8 1924.75   139.8 1913.72   149.8 1906.68   199.8 1875.66
   209.7 1870.78   219.7  1863.8   229.7 1855.66   239.7 1851.32   249.7 1849.39
   259.7 1848.76     402 1841.41     417 1840.28   419.5 1840.09   439.5 1841.24
   459.4 1844.13   529.4 1850.64   569.3 1856.95   589.3 1861.29   659.2 1872.99
   679.2 1878.06   719.1 1886.09   759.1 1895.37   769.1 1900.29     819    1918
#Mann= 3 , 0 , 0
       0      .1       0     402    .045       0     417      .1       0
Bank Sta=402,417
XS Rating Curve= 0 ,0
Exp/Cntr=0.3,0.1

Type RM Length L Ch R = 1 ,1754.6  ,337.2,341.8,347.9
XS GIS Cut Line= 3
     1953098.909      199527.151     1952666.619      199471.674
     1952263.958      199429.604
#Sta/Elev= 30
       0 1954.72    29.7 1945.35    69.3 1929.81    79.2  1922.7   128.8 1901.19
   158.5 1886.53   168.4 1877.55   178.3 1870.82     208 1855.13   217.9 1850.47
   227.8 1847.23   257.5 1843.42   307.1 1840.26   346.7 1836.23   411.4 1832.79
     416  1832.6   426.4 1832.65   534.6 1844.76   554.3 1848.66     584 1859.51
   593.8 1869.35   633.3 1892.65     663 1912.67   672.8 1923.94   682.7 1931.12
   741.9 1966.92   751.8 1975.62   761.7  1982.5   820.9 2013.63   840.7 2029.11
#Mann= 3 , 0 , 0
       0      .1       0   411.4    .045       0   426.4      .1       0
Bank Sta=411.4,426.4
XS Rating Curve= 0 ,0
Exp/Cntr=0.3,0.1

Type RM Length L Ch R = 1 ,1412.7  ,288.7,290.5,290.9
XS GIS Cut Line= 3
     1953244.582      199315.019     1952859.039      199182.833
     1952470.541      199022.155
#Sta/Elev= 30
       0  1965.8    69.6 1943.16    79.5 1937.23    99.4 1930.29   109.4 1924.54
   139.2 1915.15     159 1901.58   238.6 1859.43   248.5 1850.84   258.5 1846.14
   268.4 1842.67   278.3 1840.94   400.1 1829.16   407.6 1828.62   415.1 1828.88
   456.5 1833.21   505.3 1836.29   583.6 1846.96   593.3 1849.32   603.1 1853.39
   671.6 1875.35   681.3 1879.17   691.1 1885.43   700.9 1895.43   730.2 1920.96
   749.8 1933.87   769.3 1945.22   779.1 1952.13   788.9 1960.24     828 1982.16
#Mann= 3 , 0 , 0
       0      .1       0   400.1    .045       0   415.1      .1       0
Bank Sta=400.1,415.1
XS Rating Curve= 0 ,0
Exp/Cntr=0.3,0.1

Type RM Length L Ch R = 1 ,1122.2  ,286.2,277.1,268
XS GIS Cut Line= 3
     1953316.179      199071.361     1952757.491      198828.697
     1952490.404      198730.551
#Sta/Elev= 30
       0 1976.31    59.9 1952.73    69.9 1946.32    79.9 1941.61   149.8 1914.82
   159.8 1905.82   179.7 1895.65   189.7 1884.32   199.7 1874.97   209.7 1868.66
   229.7 1858.73   239.6  1852.2   249.6 1843.36   269.6 1836.99   279.6 1835.26
   399.4 1825.24   412.9 1825.65   427.9 1827.03   469.3 1829.92   549.2 1841.98
   589.1 1845.98   628.7 1854.75   687.6 1884.25   707.2 1900.24   775.9 1938.78
   785.7  1948.7   795.5 1955.73   864.2 1993.06     874 2002.23   893.7 2011.24
#Mann= 3 , 0 , 0
       0     .06       0   412.9    .045       0   427.9     .06       0
Bank Sta=412.9,427.9
XS Rating Curve= 0 ,0
Exp/Cntr=0.3,0.1

Type RM Length L Ch R = 1 ,845.2   ,148.5,152.8,157.2
XS GIS Cut Line= 2
     1953204.886      198669.649     1952558.084       198653.56
#Sta/Elev= 30
       0 1905.07    19.9 1900.28    39.8 1891.03    49.8  1887.4    59.7 1881.39
    69.7 1873.88    99.5 1859.75   109.5 1852.88   119.4  1844.1   139.4 1830.85
   149.3 1826.01   159.3 1823.34   166.9 1822.63   179.2 1822.41     209 1825.16
   288.7 1824.48   328.5 1826.25   408.1 1833.18     438 1837.82   447.9 1840.53
   457.9 1845.46   487.7 1856.54   497.7 1862.12   507.6 1869.36   527.6 1886.18
   537.5 1897.62   597.2  1933.9   607.2 1941.07   617.1 1953.09     647 1971.91
#Mann= 3 , 0 , 0
       0     .06       0   166.9    .045       0   179.2     .06       0
Bank Sta=166.9,179.2
XS Rating Curve= 0 ,0
Exp/Cntr=0.3,0.1

Type RM Length L Ch R = 1 ,692.3   ,159.4,158.7,158
XS GIS Cut Line= 3
       1953462.3      198652.425     1953133.988      198537.475
     1952641.309      198429.043
#Sta/Elev= 30
       0 1918.97    99.4 1910.79   149.1 1909.94   198.8 1910.76   248.5 1909.26
   278.3 1906.25   288.2 1903.62   308.1 1895.62     318 1886.33   347.8 1864.88
   377.5 1850.87   397.3 1838.13   436.9 1822.88   443.7 1821.25   456.7 1820.09
   458.7 1820.19   476.4 1822.67   486.3 1823.06     605 1822.96   644.6 1824.25
   694.1 1828.67     704 1830.74   723.7 1835.64   733.6 1839.07   743.5 1844.88
   763.3 1852.64     793 1866.91   812.8 1878.02   822.6 1889.59   852.3 1910.13
#Mann= 3 , 0 , 0
       0     .06       0   443.7    .045       0   458.7     .06       0
Bank Sta=443.7,458.7
XS Rating Curve= 0 ,0
Exp/Cntr=0.3,0.1

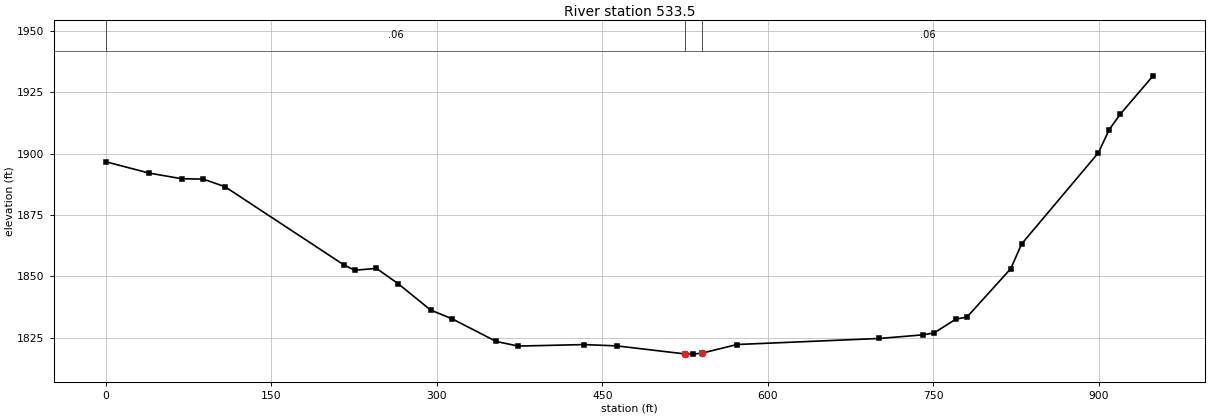
Type RM Length L Ch R = 1 ,533.5   ,496.7,533.6,570.5
XS GIS Cut Line= 3
      1953515.27      198571.461     1953275.576      198400.714
     1952631.992      198280.042
#Sta/Elev= 30
       0 1896.65    39.2 1892.04    68.7 1889.74    88.3 1889.59   107.9  1886.5
   215.8 1854.61   225.6 1852.46   245.2 1853.22   264.9 1846.97   294.3 1836.25
   314.1  1832.6   353.8 1823.43   373.7 1821.56   433.2 1822.17     463 1821.64
   525.3 1818.34   532.4 1818.28   540.3 1818.69   572.1  1822.2   701.1 1824.66
   740.8 1826.15   750.7 1826.93   770.5 1832.58   780.4 1833.36   820.1 1853.08
     830 1863.19   899.5 1900.29   909.4 1909.79   919.3    1916   949.1 1931.67
#Mann= 3 , 0 , 0
       0     .06       0   525.3    .045       0   540.3     .06       0
Bank Sta=525.3,540.3
XS Rating Curve= 0 ,0
Exp/Cntr=0.3,0.1

Chan Stop Cuts=-1
Use User Specified Reach Order=0
Composite Channel Slope=5